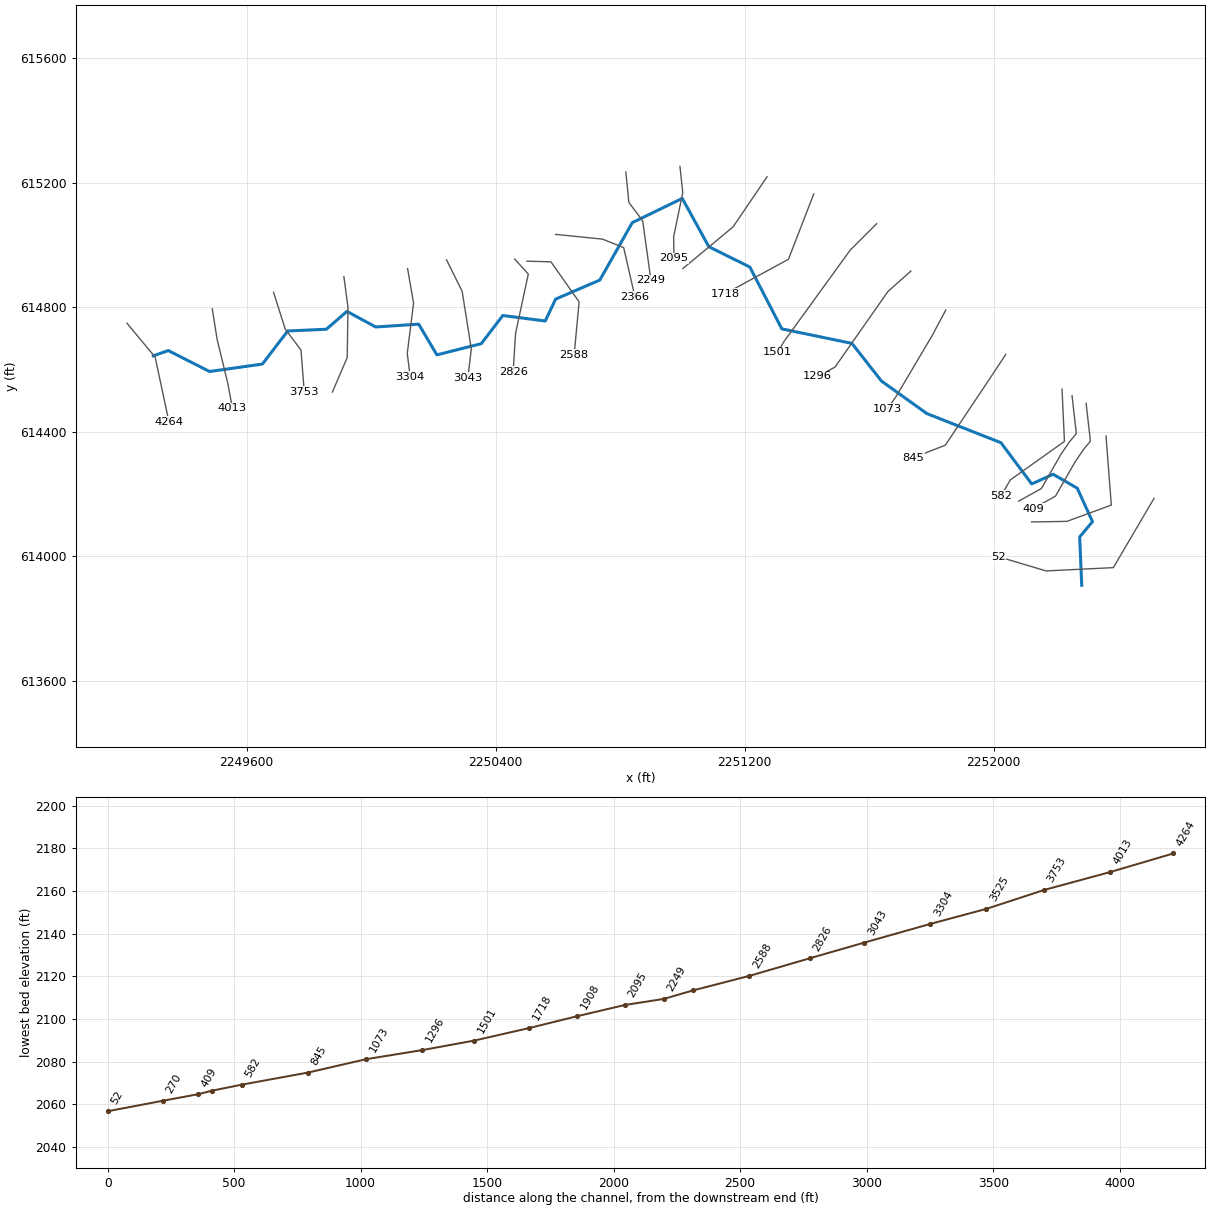
--- RAFERN.prj (project) ---

Proj Title=RAFERN
Current Plan=p01
Default Exp/Contr=0,0
English Units
Geom File=g01
Flow File=f01
Plan File=p01
BEGIN DESCRIPTION:
----------MODEL BY WOOD PLC 2022----------
AFH study
Randolph County, WV
HEC-RAS Version: RAS 6.2
Vertical Datum: NAVD88
Projection: NAD 1983 StatePlane West Virginia S FIPS 4702 (US Feet)
Terrain: 1-meter LIDAR (FEMA Region III 3DEP collected 2016-2018)
Land Use: 2019 NLCD
Hydrologic Method:
WV SIR2010-5033 regression equations
Additional Model Notes:
None
END DESCRIPTION:
DSS Export Rating Curves= 0
DSS Export Rating Curve Sorted= 0
DSS Export Volume Flow Curves= 0
DXF OffsetX= 0
DXF OffsetY= 0
DXF ScaleX= 0
DXF ScaleY= 0

--- RAFERN.p01 (plan) ---

Plan Title=Floodplain
Program Version=6.20
Short Identifier=Floodplain
Geom File=g01
Flow File=f01
Subcritical Flow
K Sum by GR= 0
Std Step Tol= 0.01
Critical Tol= 0.01
Num of Std Step Trials= 20
Max Error Tol= 0.3
Flow Tol Ratio= 0.001
Split Flow NTrial= 30
Split Flow Tol= 0.02
Split Flow Ratio= 0.02
Log Output Level= 0
Friction Slope Method= 1
Unsteady Friction Slope Method= 2
Unsteady Bridges Friction Slope Method= 1
Parabolic Critical Depth
Global Vel Dist= 0 , 0 , 0
Global Log Level= 0
CheckData=True
Encroach Param=-1 ,0,0, 0
Mapping Interval=1HOUR
Computation Time Step Use Courant=        0
Computation Time Step Use Time Series=    0
Computation Time Step Count To Double=0
Computation Time Step Max Doubling=0
Computation Time Step Max Halving=0
Computation Time Step Residence Courant=0
Run HTab= 0
Run UNet= 0
Run Sediment= 0
Run PostProcess= 0
Run WQNet= 0
Run RASMapper=-1
UNET Theta= 0
UNET Theta Warmup= 0
UNET ZTol= 0
UNET ZSATol= 0
UNET MxIter= 0
UNET Max Iter WO Improvement= 0
UNET MaxInSteps= 0
UNET DtIC= 0
UNET DtMin= 0
UNET MaxCRTS= 0
UNET WFStab= 0
UNET SFStab= 0
UNET WFX= 1
UNET SFX= 1
UNET Gravity=32.174
UNET 1D Methodology=Finite Difference
UNET DSS MLevel= 1
UNET Pardiso=0
UNET DZMax Abort= 0
UNET Use Existing IB Tables= 0
UNET Froude Reduction=False
UNET Froude Limit= 0
UNET Froude Power= 0
UNET D1 Cores= 0
UNET WindReference=Eulerian
UNET WindDragFormulation=Hsu (1988)
UNET D2 Coriolis=0
UNET D2 Cores= 0
UNET D2 Theta= 1
UNET D2 Theta Warmup= 1
UNET D2 Z Tol= 0.01
UNET D2 Volume Tol= 0.01
UNET D2 Max Iterations= 20
UNET D2 Equation= 0
UNET D2 RampUpFraction=0.1
UNET D2 TimeSlices= 1
UNET D2 Turbulence Formulation=Non-Conservative (original)
UNET D2 Eddy Viscosity=0.3
UNET D2 Transverse Eddy Viscosity=0.1
UNET D2 Smagorinsky Mixing=0
UNET D2 BCVolumeCheck=0
UNET D2 Cores=0
UNET D2 SolverType=PARDISO (Direct)
UNET D2 Minimum Iterations= 2147483647
UNET D2 Maximum Iterations= 2147483647
UNET D2 Restart Number= 10
UNET D2 Relaxation Coeff=1.3
UNET D2 SOR Precondition Iterations= 10
UNET D2 ILUT Maximum Fill= 8
UNET D2 ILUT Tolerance=1E-08
UNET D1D2 MaxIter= 0
UNET D1D2 ZTol=0.01
UNET D1D2 QTol=0.1
UNET D1D2 MinQTol=1
Write IC File= 0
Write IC File at Fixed DateTime=0
Write IC File at Sim End=0
Echo Input=False
Echo Parameters=False
Echo Output=False
Write Detailed= 0
HDF Write Warmup=0
HDF Write Time Slices=0
HDF Flush=0
HDF Compression= 1
HDF Chunk Size= 1
HDF Spatial Parts= 1
HDF Use Max Rows=0
HDF Fixed Rows= 1
Calibration Method= 0
Calibration Iterations= 20
Calibration Max Change=0.05
Calibration Tolerance=0.2
Calibration Maximum=1.5
Calibration Minimum=0.5
Calibration Optimization Method= 1
WQ AD Non Conservative
WQ ULTIMATE=-1
WQ Max Comp Step=1HOUR
WQ Output Interval=15MIN
WQ Output Selected Increments= 0
WQ Output face flow=0
WQ Output face velocity=0
WQ Output face area=0
WQ Output face dispersion=0
WQ Output cell volume=0
WQ Output cell surface area=0
WQ Output cell continuity=0
WQ Output cumulative cell continuity=0
WQ Output face conc=0
WQ Output face dconc_dx=0
WQ Output face courant=0
WQ Output face peclet=0
WQ Output face adv mass=0
WQ Output face disp mass=0
WQ Output cell mass=0
WQ Output cell source sink temp=0
WQ Output nsm pathways=0
WQ Output nsm derived pathways=0
WQ Create Restart=0
WQ Fixed Restart=0
WQ System Summary=0
WQ Write To DSS=0
Sorting and Armoring Iterations= 10
XS Update Threshold= 0.02
Bed Roughness Predictor= 0
Hydraulics Update Threshold= 0.02
Energy Slope Method= 1
Volume Change Method= 1
Sediment Retention Method= 0
Sediment TS Multiplier= 1
Warm Up Method= 0
XS Weighting Method= 0
Number of US Weighted Cross Sections= 1
Number of DS Weighted Cross Sections= 1
Upstream XS Weight=0
Main XS Weight=1
Downstream XS Weight=0
Number of DS XS's Weighted with US Boundary= 1
Upstream Boundary Weight= 1
Weight of XSs Associated with US Boundary= 0
Number of US XS's Weighted with DS Boundary= 1
Downstream Boundary Weight= 0.5
Weight of XSs Associated with DS Boundary= 0.5
Percentile Method= 0
Sediment Output Level= 3
Mass or Volume Output= 0
Output Increment Type= 1
Profile and TS Output Increment= 1
Transport Output Increment 1
XS Output Flag= 0
XS Output Increment= 10
Read HDF5 Sediment Hotstart= 0
Sediment Hotstart Type= 0
Write Gradation File= 0
Read Gradation Hotstart= 0
Write HDF5 File= 1
Write Binary Output= 1
Write DSS Sediment File= 0
DSS Sediment Output Type= 1
SV Curve= 0
Specific Gage Flag= 0
Subcell Erosion Methods= 0
Subcell Deposition Methods= 0
Advection Scheme= 1
Matrix Solver= 0
Implicit Weighting Factor= 1
Maximum Outer Loop Convergence Iterations= 5
Convergence Maximum Absolute= 0.001
Convergence RMSE= 0.0001
Grain Fractions Max Abs Error= 0.001
Max Subgrid Regions= 1
Max Subgrid Length Scale= 3.402823E+38
Initial Layer Thickness= 3.402823E+38
Min Layer Thickness= 3.402823E+38
Max Layer Thickness= 3.402823E+38
Number of Layers= 5

--- RAFERN.f01 (steady flow) ---

Flow Title=Flow
Program Version=6.20
Number of Profiles= 1
Profile Names=P100yr
River Rch & RM=RAFERN,Main,4264
     560
Boundary for River Rch & Prof#=RAFERN,Main            , 1
Up Type= 0
Dn Type= 3
Dn Slope=0.02258
DSS Import GetInterval= 0
DSS Import GetPeak= 0
DSS Import FillOption= 0

--- RAFERN.g01 (geometry) ---

Geom Title=Geometry
Program Version=6.20

River Reach=RAFERN          ,Main
Reach XY= 30
     2249300.305      614644.115     2249348.249      614661.153
     2249480.861      614593.768     2249650.565       614617.64
     2249732.163      614723.976     2249856.087      614729.551
     2249922.267       614786.91     2250014.606      614736.845
      2250152.84      614745.926     2250211.113      614647.225
2250353.88997142614683.2645584462250422.98207811614773.686681187
     2250559.269      614756.084     2250592.691      614826.419
     2250734.603      614887.509     2250838.934      615072.067
     2250999.524      615149.7582251084.68791307614994.734024744
     2251216.505      614929.321     2251319.243      614730.692
     2251544.449       614684.04     2251639.279      614563.223
2251785.00903801614458.694781074     2252023.113      614365.074
     2252121.918      614232.5432252190.61686634614263.693614404
2252268.20365185614218.9847419042252317.19819216614111.482431166
      2252275.92      614062.448      2252282.61       613906.82

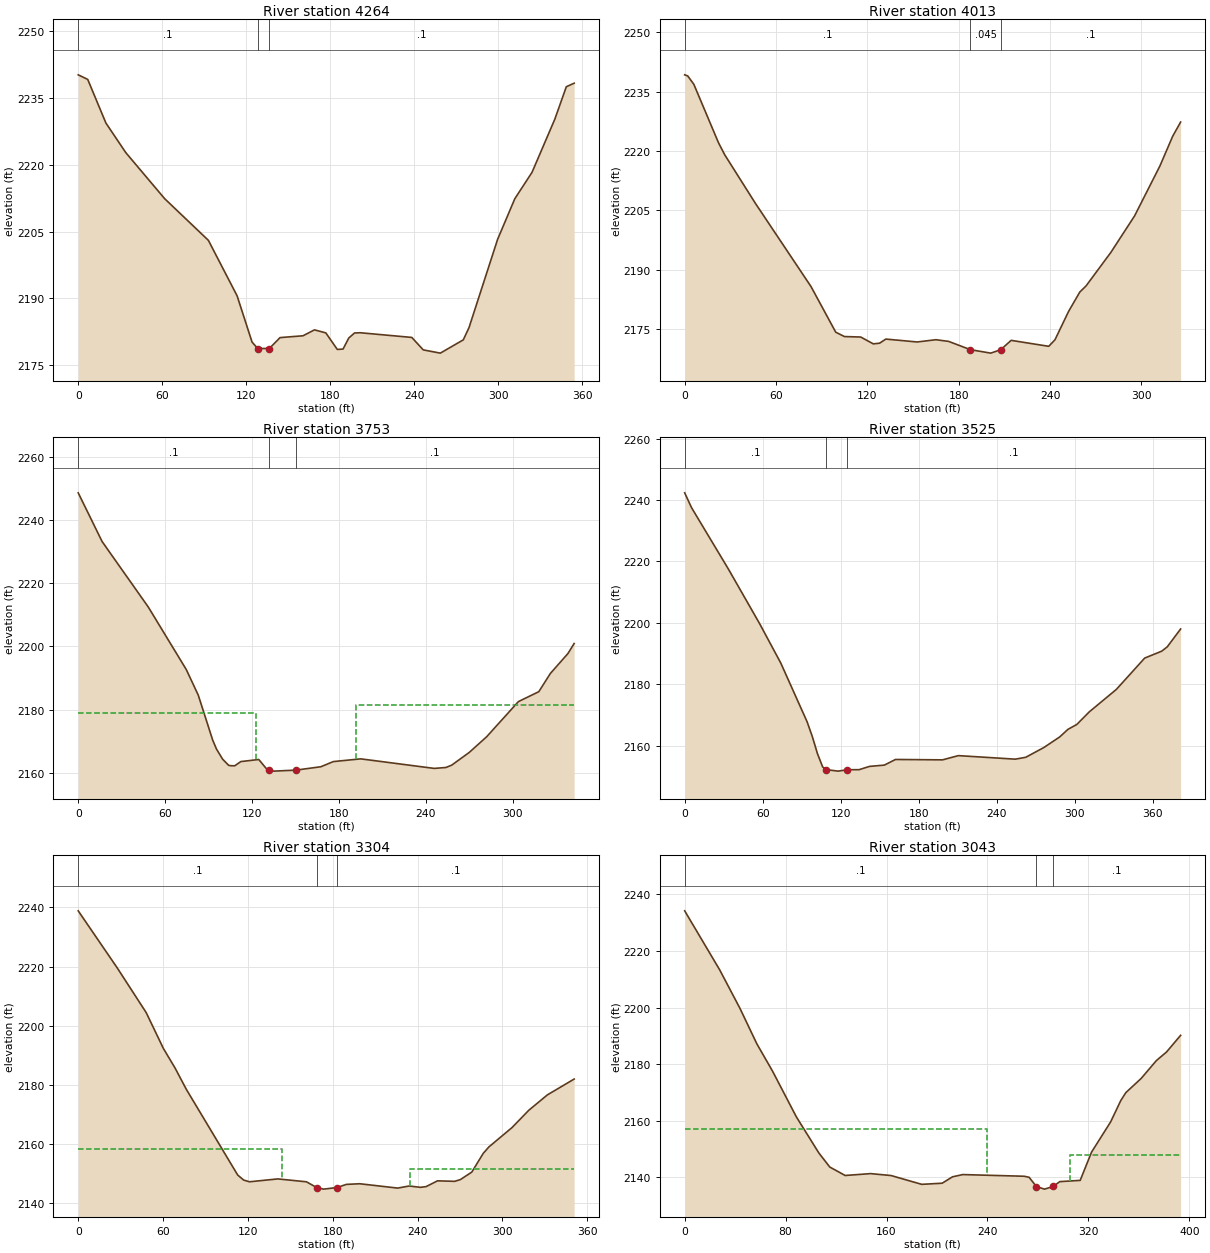
Type RM Length L Ch R = 1 ,4264    ,250.4,251.1,253.9
XS GIS Cut Line= 3
2249215.83847111614748.6850919552249306.16796307614640.035430142
2249350.62856193614431.697190351
#Sta/Elev= 30
       0 2240.23     6.8  2239.2    19.8 2229.39      34 2222.74    61.8 2212.38
      93 2203.03   113.5 2190.57   124.2 2180.16  128.272178.716  136.542178.717
   144.2 2181.17   160.6 2181.58   168.8 2182.91   176.9 2182.23   185.1 2178.51
   189.2 2178.59   193.3 2181.08   197.4 2182.21   201.5 2182.26   238.3 2181.21
   246.5 2178.41   258.7 2177.68   275.1 2180.66   279.2 2183.42   299.6 2203.24
   311.9 2212.38   324.2 2218.31   340.5 2230.27   348.7 2237.55   354.3 2238.35
#Mann= 3 ,-1,0
       0      .1       0  128.27    .045       0  136.54      .1       0
Bank Sta=128.27,136.54
XS Rating Curve= 0 ,0
Exp/Cntr(USF)=0,0
Exp/Cntr=0.3,0.1

Type RM Length L Ch R = 1 ,4013    ,256.2,260.3,263.4
XS GIS Cut Line= 4
 2249489.6831395614795.1188714872249505.28543366614697.057271569
2249539.74259158614554.7599578832249554.32123126614476.092995877
#Sta/Elev= 30
       0 2239.25       2 2238.97       6 2236.87    22.2 2222.09    26.3 2219.04
    46.5 2206.73      83 2185.71    99.2  2174.2   104.9 2173.09   115.6 2172.97
   123.9 2171.24     128 2171.41   132.1 2172.45   152.7 2171.72     165 2172.29
   173.3 2171.87   187.7 2169.77     201  2168.9   207.6 2169.77   214.4 2172.13
   239.1 2170.62   243.2 2172.28   252.1 2179.43   259.5 2184.34   263.6 2185.89
   279.9 2194.37   295.5 2203.61   312.1 2216.21   320.5 2223.73   325.7 2227.31
#Mann= 3 ,-1,0
       0      .1       0   187.7    .045       0   207.6      .1       0
Bank Sta=187.7,207.6
XS Rating Curve= 0 ,0
Exp/Cntr(USF)=0,0
Exp/Cntr=0.3,0.1

Type RM Length L Ch R = 1 ,3753    ,229.1,227.6,215.3
XS GIS Cut Line= 4
2249686.47672117614848.2223367992249724.13283375 614729.83568192
2249774.69458194614662.5725790762249785.13201495614528.817935317
#Sta/Elev= 30
       0 2248.58    16.5 2233.17    48.4 2212.44    74.6 2192.69    82.9 2184.58
    92.9 2170.31    95.5  2167.5    99.7 2164.32   103.9 2162.35   105.7 2162.22
   108.1 2162.21   112.3 2163.54   124.7  2164.2   130.4 2161.06  131.63 2160.85
   135.1 2160.52   150.4 2160.84   167.6 2161.91   176.2 2163.54   195.1  2164.4
   245.9 2161.38   253.9 2161.67   257.9  2162.4     270 2166.42     282 2171.36
     304 2182.52   318.1 2185.66   326.1 2191.44   338.2 2197.72   342.5  2200.9
#Mann= 3 ,-1,0
       0      .1       0  131.63    .045       0   150.4      .1       0
#XS Ineff= 2 , 0
          122.82 2178.79  191.55         2181.55
Permanent Ineff=
       F       F
Bank Sta=131.63,150.4
XS Rating Curve= 0 ,0
Exp/Cntr(USF)=0,0
Exp/Cntr=0.3,0.1

Type RM Length L Ch R = 1 ,3525    ,221.2,221.2,218.9
XS GIS Cut Line= 4
2249912.48821711614898.4424415332249925.60899282614800.036623733
2249923.14884738614638.4870728462249875.54463642614527.807248623
#Sta/Elev= 30
       0 2242.36     5.3 2237.51    33.6 2217.53    57.8  2199.6    73.9 2186.89
    94.1 2167.78    98.1    2163   102.1 2157.36   106.1 2153.04  109.022152.142
   118.1 2151.68  124.892152.141   134.1 2152.15   142.1 2153.22   153.5 2153.64
   162.1 2155.48   198.2 2155.35   210.4 2156.73   254.2 2155.58   262.3  2156.2
   276.3 2159.41   288.4 2162.84   294.6 2165.27   301.5 2166.89   311.1    2171
   331.9 2178.31   353.7 2188.52   366.8 2190.77   371.1 2192.21   381.3    2198
#Mann= 3 ,-1,0
       0      .1       0  109.02    .045       0  124.89      .1       0
Bank Sta=109.02,124.89
XS Rating Curve= 0 ,0
Exp/Cntr(USF)=0,0
Exp/Cntr=0.3,0.1

Type RM Length L Ch R = 1 ,3304    ,257.2,261.1,260.8
XS GIS Cut Line= 4
2250117.10370538614924.5474388782250136.29372895614813.344270925
2250116.04002619614651.8022003152250125.42506015614577.310974473
#Sta/Elev= 30
       0 2238.86    27.8 2219.39    48.1 2204.38    60.2 2192.29    68.4 2185.71
    76.5 2178.38   112.8 2149.39     117  2147.7   121.1 2147.12   141.2 2148.09
   161.4 2147.11  168.71 2145.15   173.5 2144.63     1832145.164   189.6 2146.23
   199.1 2146.45   225.9 2144.98     234 2145.69     242 2145.24     246 2145.48
   254.1 2147.44   266.2 2147.27   270.2 2147.85   278.3 2150.39   286.4 2156.73
   290.4 2158.91   306.8 2165.49   318.6 2171.32   331.8 2176.55   350.7  2181.9
#Mann= 3 ,0,0
       0      .1       0  168.71    .045       0     183      .1       0
#XS Ineff= 2 , 0
          144.12 2158.28  234.79         2151.54
Permanent Ineff=
       F       F
Bank Sta=168.71,183
XS Rating Curve= 0 ,0
Exp/Cntr(USF)=0,0
Exp/Cntr=0.3,0.1

Type RM Length L Ch R = 1 ,3043    ,224.2,216.8,214.2
XS GIS Cut Line= 4
2250242.23507733614952.4522222592250292.34824004614851.414048833
2250321.76444514614666.2632566282250310.79933088614574.057251365
#Sta/Elev= 30
       0 2234.19    27.8  2213.3    43.8 2199.75    57.2 2187.21    69.6 2177.59
    88.5 2161.42   106.3 2148.68     115 2143.68   127.2 2140.69   147.4 2141.35
   163.6 2140.67   187.9 2137.56   204.1 2137.96   212.3 2140.22   220.4 2141.01
     269 2140.42     273 2140.06   278.8 2136.77   285.2 2135.87  292.192136.813
   297.3 2138.52   313.5 2138.96   322.5 2148.94   337.6  2159.6   345.7 2167.18
   349.7 2169.97   361.8 2174.96   373.9 2181.29   381.9  2184.3   393.1  2190.2
#Mann= 3 ,-1,0
       0      .1       0   278.8    .045       0  292.19      .1       0
#XS Ineff= 2 , 0
          239.42 2157.03  305.11         2147.96
Permanent Ineff=
       F       F
Bank Sta=278.8,292.19
XS Rating Curve= 0 ,0
Exp/Cntr(USF)=0,0
Exp/Cntr=0.3,0.1

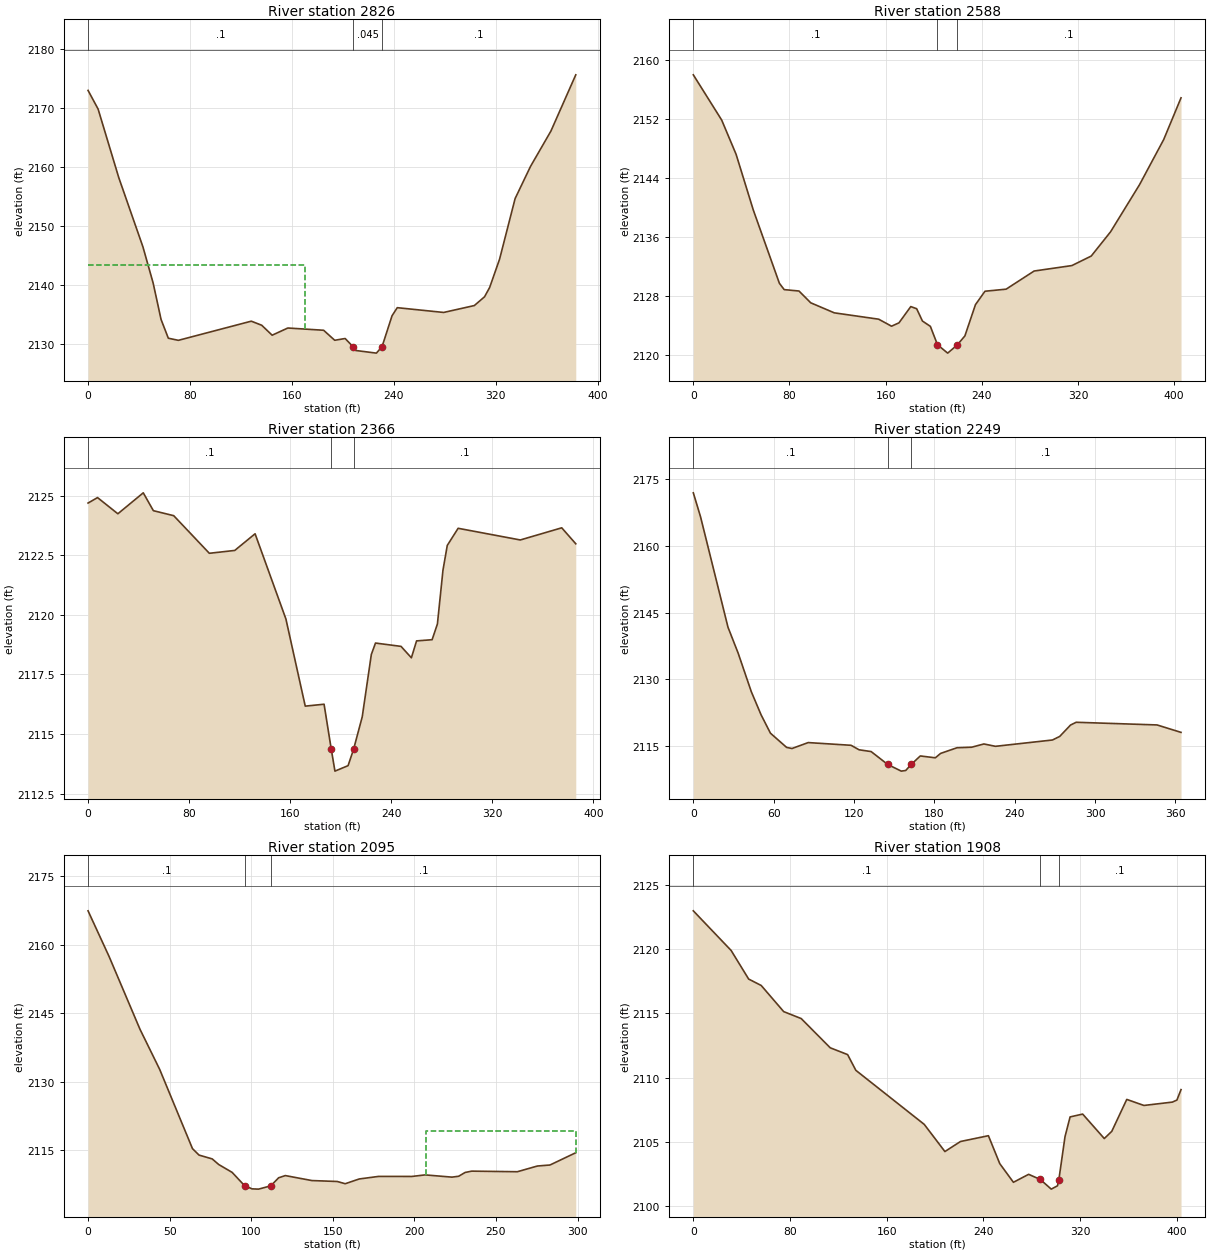
Type RM Length L Ch R = 1 ,2826    ,220,238.2,241.1
XS GIS Cut Line= 4
2250461.11155056614955.0544621732250504.83314249614906.789715695
2250463.92546455614716.2544395752250456.16461108614593.717593157
#Sta/Elev= 30
       0 2173.03     7.9 2169.86    24.1 2158.24    43.1 2146.47    51.1 2140.34
    57.3 2134.18      63 2130.99    70.9 2130.63   128.1 2133.88   136.3 2133.19
   144.5  2131.5   156.8 2132.72   184.9 2132.34   193.6 2130.64   201.8 2130.94
  207.972129.554     210 2128.91   226.3 2128.46  230.762129.556   238.6  2134.8
   242.7 2136.17   279.1 2135.36   303.2 2136.53   311.2 2138.02   315.2 2139.59
     323  2144.4   335.2 2154.68   347.3 2160.14   363.3 2166.13   382.8 2175.67
#Mann= 3 ,-1,0
       0      .1       0  207.97    .045       0  230.76      .1       0
#XS Ineff= 2 , 0
          170.11 2143.38
Permanent Ineff=
       F       F
Bank Sta=207.97,230.76
XS Rating Curve= 0 ,0
Exp/Cntr(USF)=0,0
Exp/Cntr=0.3,0.1

Type RM Length L Ch R = 1 ,2588    ,216.1,221.6,225.7
XS GIS Cut Line= 4
2250500.60990608614948.1595383142250577.55272658614946.134727249
2250668.06917178614817.5592245682250652.11705777614646.821879738
#Sta/Elev= 30
       0 2157.96    23.6 2151.83    35.6 2147.18    49.9 2139.63    71.6  2129.7
    75.6 2128.84    87.9 2128.65    97.7 2127.05   117.3 2125.69   154.2 2124.83
   164.9 2123.88   171.1 2124.34   180.9 2126.54   185.8 2126.25   190.6 2124.58
   197.2 2123.86   203.12121.369   211.6 2120.23   219.6 2121.35   225.9 2122.56
   234.7  2126.8   242.6 2128.62   260.2  2128.9   283.5 2131.36   314.9  2132.1
     331 2133.39   347.1 2136.68   371.2 2143.07   391.3 2149.19   405.7 2154.84
#Mann= 3 ,-1,0
       0      .1       0   203.1    .045       0   219.6      .1       0
Bank Sta=203.1,219.6
XS Rating Curve= 0 ,0
Exp/Cntr(USF)=0,0
Exp/Cntr=0.3,0.1

Type RM Length L Ch R = 1 ,2366    ,122.5,117.5,112.9
XS GIS Cut Line= 4
2250592.68594656615034.2987836612250743.43313041615019.011460114
2250811.26430112614991.6765107252250847.20469754614834.348690909
#Sta/Elev= 30
       0  2124.7     7.5 2124.93    23.6 2124.25    43.7 2125.13    51.7 2124.38
    67.8 2124.17      96 2122.59   116.1 2122.71   132.2 2123.41   156.6 2119.83
   171.9 2116.17   186.8 2116.25   192.52114.358   195.4 2113.44   205.8 2113.67
  210.152114.357     217 2115.72   224.2 2118.34   227.5 2118.82   247.7 2118.68
   255.9  2118.2     260 2118.91   272.3 2118.96   276.5 2119.62   280.9 2121.88
   284.3 2122.92   292.9 2123.64   342.1 2123.15   374.9 2123.66     386 2122.99
#Mann= 3 ,-1,0
       0      .1       0   192.5    .045       0  210.15      .1       0
Bank Sta=192.5,210.15
XS Rating Curve= 0 ,0
Exp/Cntr(USF)=0,0
Exp/Cntr=0.3,0.1

Type RM Length L Ch R = 1 ,2249    ,160.1,153.5,146.2
XS GIS Cut Line= 4
2250818.07659802615234.5108931962250827.83460317615137.094226353
2250872.32697712615077.632579209 2250898.6606874614887.447362932
#Sta/Elev= 30
       0  2171.9     5.4 2166.52    25.9 2141.72    33.5 2135.89    43.3 2127.25
    50.6 2122.06    57.6 2117.93    69.7 2114.73    73.7 2114.49    85.8 2115.82
   117.8 2115.21   123.8  2114.2   132.8  2113.8  145.14 2110.91   155.3 2109.41
   158.6 2109.55   162.7 2110.91   169.5 2112.82   180.7  2112.4   184.7 2113.39
   196.9 2114.66   207.9 2114.78     217 2115.51   225.6 2114.98   268.2  2116.4
   273.6  2117.2   281.7 2119.76   285.9 2120.38   346.3 2119.78   364.2 2118.11
#Mann= 3 ,0,0
       0      .1       0  145.14    .045       0   162.7      .1       0
Bank Sta=145.14,162.7
XS Rating Curve= 0 ,0
Exp/Cntr(USF)=0,0
Exp/Cntr=0.3,0.1

Type RM Length L Ch R = 1 ,2095    ,192.1,187.3,181
XS GIS Cut Line= 4
2250991.92923624615252.8205054522251001.04088604 615168.79084622
2250971.68112558615026.0416660772250972.89601222614957.400570945
#Sta/Elev= 30
       0 2167.36    12.9 2157.38    31.8 2141.51    43.9 2132.72      64 2115.41
      68    2114    76.1 2113.16    80.1 2111.93    88.3 2110.22   95.892107.329
   100.5 2106.62   104.5 2106.56     112 2107.28   116.8 2109.04   120.9 2109.52
   137.2 2108.43   152.7 2108.23   157.6 2107.74   166.2 2108.78   178.1 2109.34
   198.5 2109.33   206.6 2109.67     223 2109.18   227.1 2109.37   231.1  2110.2
   235.1 2110.49   263.1 2110.36   275.4 2111.61   283.1 2111.83   298.9 2114.51
#Mann= 3 ,-1,0
       0      .1       0   95.89    .045       0     112      .1       0
#XS Ineff= 2 , 0
                          206.81         2119.36
Permanent Ineff=
       F       F
Bank Sta=95.89,112
XS Rating Curve= 0 ,0
Exp/Cntr(USF)=0,0
Exp/Cntr=0.3,0.1

Type RM Length L Ch R = 1 ,1908    ,192.8,190.1,188.6
XS GIS Cut Line= 3
 2251271.7320045615219.0721277782251162.52350962615058.270834066
2251001.57812519614924.559520319
#Sta/Elev= 30
       0 2122.96    31.3 2119.88    45.8 2117.66    56.2 2117.16    74.8 2115.13
    89.3 2114.59   113.3 2112.32   127.7 2111.79   134.5 2110.57   191.1 2106.37
   208.2 2104.26   221.1 2105.04   244.2 2105.49   253.6 2103.32   264.9 2101.87
   277.5 2102.49  287.14 2102.09   296.2 2101.34   301.4  2101.6   302.5 2102.07
   307.6 2105.42   311.8 2106.95   322.2 2107.17   340.1 2105.27   346.3 2105.83
   358.7 2108.31   372.9 2107.84   396.4  2108.1   400.2 2108.26   403.6 2109.07
#Mann= 3 ,0,0
       0      .1       0  287.14    .045       0   302.5      .1       0
Bank Sta=287.14,302.5
XS Rating Curve= 0 ,0
Exp/Cntr(USF)=0,0
Exp/Cntr=0.3,0.1

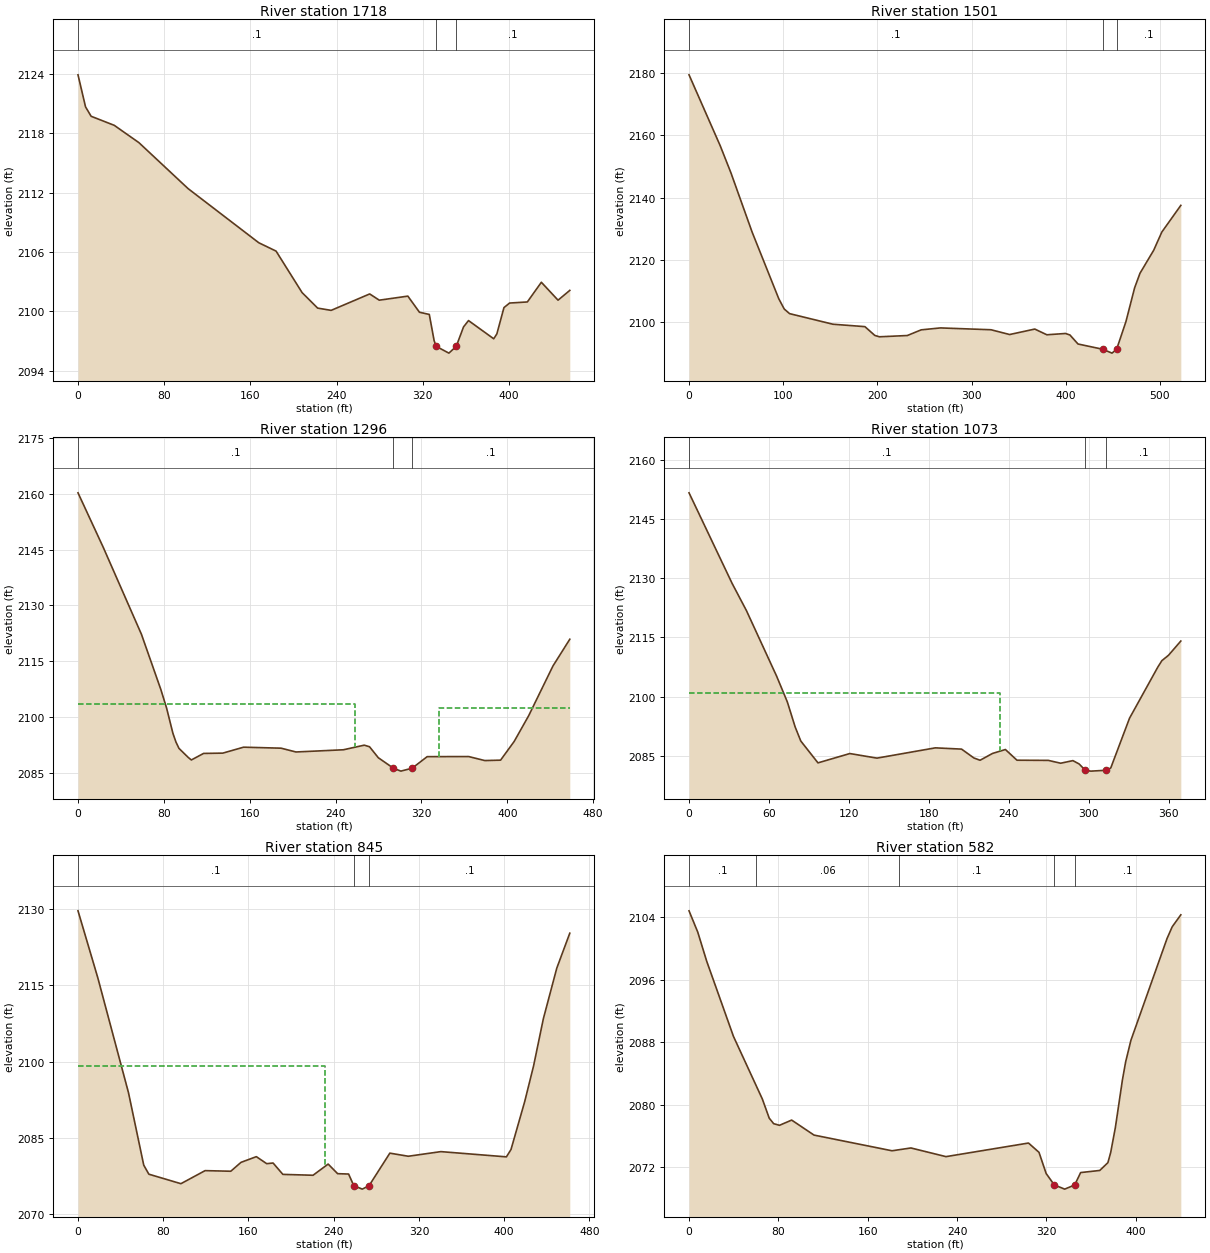
Type RM Length L Ch R = 1 ,1718    ,211.5,217.1,218.2
XS GIS Cut Line= 3
2251421.94839245615164.5118461932251340.46112546614954.279160687
2251137.54730844614843.951372577
#Sta/Elev= 30
       0 2123.89       7 2120.65    12.2  2119.7    33.6 2118.79    56.5 2117.04
   102.2 2112.39   167.8 2106.92   183.8 2106.08     208 2101.88   222.4 2100.32
   234.9 2100.09   270.7 2101.75   279.6 2101.12   306.1 2101.53   316.9  2099.9
     326 2099.68   330.5 2097.03   332.52096.448   344.2 2095.77     351 2096.45
   357.8 2098.42   362.4 2099.06   385.8 2097.22   388.7 2097.71   395.3 2100.37
   400.5 2100.83     417 2100.94     430 2102.93   445.5 2101.12   456.4 2102.11
#Mann= 3 ,0,0
       0      .1       0   332.5    .045       0     351      .1       0
Bank Sta=332.5,351
XS Rating Curve= 0 ,0
Exp/Cntr(USF)=0,0
Exp/Cntr=0.3,0.1

Type RM Length L Ch R = 1 ,1501    ,202.2,204.8,201.2
XS GIS Cut Line= 4
 2251623.7616947615068.5653054972251538.98176967614983.873438941
2251327.03215917614691.2908244422251305.76471266614656.024460291
#Sta/Elev= 30
       0 2179.54    33.2 2156.64    44.6 2147.89      67 2128.88    95.3 2107.42
   101.1  2104.1   106.8 2102.61   152.8  2099.2   186.8 2098.42   197.3 2095.59
   202.2 2095.15   231.8 2095.56   246.6 2097.39     267 2098.01   320.7 2097.42
   340.5 2095.88   367.2 2097.64     380  2095.8   399.8 2096.22   404.5 2095.74
   413.1 2092.83   439.22091.152   449.2 2089.89   454.1 2091.11     464 2100.04
   473.2 2110.89   478.9  2115.6   493.5 2123.04   502.1 2128.88   522.3 2137.49
#Mann= 3 ,0,0
       0      .1       0   439.2    .045       0   454.1      .1       0
Bank Sta=439.2,454.1
XS Rating Curve= 0 ,0
Exp/Cntr(USF)=0,0
Exp/Cntr=0.3,0.1

Type RM Length L Ch R = 1 ,1296    ,221.5,222.8,222.3
XS GIS Cut Line= 4
  2251733.773816614916.4548523992251660.07069321614850.850973865
2251489.98656368614607.8736459632251434.30425937614578.513885508
#Sta/Elev= 30
       0 2160.28    23.6 2145.57    59.1 2122.24    77.1 2107.46    82.5 2102.44
    88.4 2095.64    91.3 2093.23    94.1 2091.55   102.7 2089.12   105.6 2088.44
     117  2090.2   134.9 2090.28   154.3 2091.88   189.2 2091.61   203.1 2090.59
   247.2 2091.18   266.7 2092.42   271.6    2092   279.8 2089.04   293.8 2086.24
   300.8 2085.44  311.35 2086.23   325.3 2089.33     364 2089.36     379 2088.28
   393.7 2088.39   406.4 2093.43   419.9 2100.35   442.5 2113.71   458.2 2120.91
#Mann= 3 ,0,0
       0      .1       0   293.8    .045       0  311.35      .1       0
#XS Ineff= 2 , 0
          257.76 2103.43   336.1          2102.5
Permanent Ineff=
       F       F
Bank Sta=293.8,311.35
XS Rating Curve= 0 ,0
Exp/Cntr(USF)=0,0
Exp/Cntr=0.3,0.1

Type RM Length L Ch R = 1 ,1073    ,228.2,228.7,228
XS GIS Cut Line= 4
2251845.86499929614791.2501546892251802.80238543614710.339786251
2251686.56930979614514.0454373832251658.30138512614473.518165334
#Sta/Elev= 30
       0 2151.59    32.4 2128.63    43.1 2121.78    65.8 2105.16    73.8 2098.67
    79.7 2092.31    83.9 2088.78    96.8 2083.25   120.7 2085.61   141.1 2084.45
   184.9 2087.05   204.6 2086.73   213.9 2084.48   218.5 2083.91   227.8 2085.63
   237.5 2086.63   246.2 2083.92   269.7 2083.88     279 2083.16   288.2 2083.82
   292.9 2082.96   297.5 2081.37   301.7 2081.16   313.4 2081.38   316.6 2081.96
   330.7 2094.56   351.9 2107.47     355 2109.13   359.9 2110.46   369.2 2114.08
#Mann= 3 ,-1,0
       0      .1       0   297.5    .045       0   313.4      .1       0
#XS Ineff= 2 , 0
          233.65 2100.83
Permanent Ineff=
       F       F
Bank Sta=297.5,313.4
XS Rating Curve= 0 ,0
Exp/Cntr(USF)=0,0
Exp/Cntr=0.3,0.1

Type RM Length L Ch R = 1 ,845     ,265.7,262.8,259.3
XS GIS Cut Line= 4
2252038.50504761614648.7127654292251990.63203517614576.115696991
2251844.51614068614357.2114457492251740.84513554614316.441753296
#Sta/Elev= 30
       0 2129.68    18.6 2116.49    47.4 2093.88    61.7 2079.63    66.5 2077.85
    96.6 2075.98   119.3 2078.55   143.4 2078.43     153 2080.18   167.4  2081.3
   177.1 2079.92   183.1 2080.05   192.3 2077.81   220.6 2077.64   234.8 2079.84
   243.7 2077.95     254 2077.88   258.8 2075.61   266.8 2074.91   273.2 2075.59
   292.7 2081.99     310 2081.38   340.6 2082.29   402.1 2081.26   406.4  2082.7
   419.3 2092.16   427.6 2099.16   436.8 2108.46   449.4 2118.41   461.6 2125.28
#Mann= 3 ,-1,0
       0      .1       0   258.8    .045       0   273.2      .1       0
#XS Ineff= 2 , 0
          231.77 2099.17
Permanent Ineff=
       F       F
Bank Sta=258.8,273.2
XS Rating Curve= 0 ,0
Exp/Cntr(USF)=0,0
Exp/Cntr=0.3,0.1

Type RM Length L Ch R = 1 ,582     ,115.9,118.4,124.4
XS GIS Cut Line= 4
2252219.32310506614536.9401250712252227.06399723 614369.21157434
2252053.09525153614245.5349638752252023.31916453 614194.49649018
#Sta/Elev= 30
       0 2104.84     7.8 2102.12    15.8  2098.4    39.8 2088.76    65.7 2080.73
    71.8  2078.3    75.8 2077.59      81 2077.38    91.9 2078.05   111.9 2076.13
   181.8 2074.12   198.7 2074.48   230.1 2073.37     304 2075.11   313.4 2073.92
   319.8 2071.21   327.12069.746   336.4 2069.21  345.34 2069.74   350.7 2071.33
   367.8  2071.6   375.1  2072.6   377.6  2073.9   381.8 2077.11   388.1 2083.19
     391 2085.51   395.7 2088.26   428.1 2101.31   432.7  2102.8   440.4 2104.33
#Mann= 5 ,-1,0
       0      .1       0      60     .06       0  187.91      .1       0
   327.1    .045       0  345.34      .1       0
Bank Sta=327.1,345.34
XS Rating Curve= 0 ,0
Exp/Cntr(USF)=0,0
Exp/Cntr=0.3,0.1

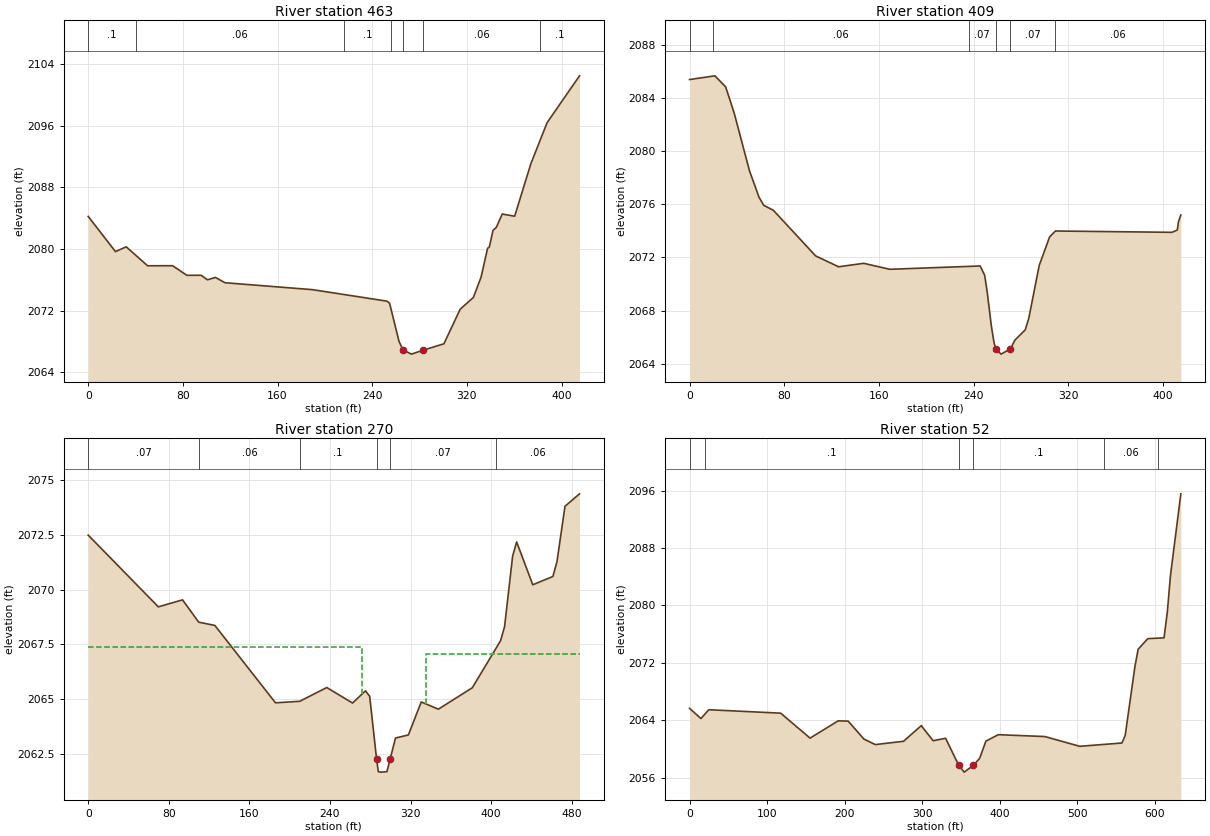
Type RM Length L Ch R = 1 ,463     ,52.4,54.3,53.9
XS GIS Cut Line= 6
2252251.43830319614516.0125292092252265.23932021614394.563579459
2252243.15769298614367.8816132262252215.55565895614327.398629976
2252152.99104847 614217.910561642252080.30569218 614177.42757839
#Sta/Elev= 30
       0 2084.22      23 2079.66    32.1 2080.28    50.2 2077.82    71.3 2077.83
    83.4 2076.58    95.4 2076.59   100.8    2076   107.5 2076.31   115.6 2075.62
   189.7 2074.72   252.5 2073.23   254.7 2072.96   262.7 2067.99  266.032066.912
   273.1 2066.36   283.2 2066.88   300.6  2067.7   314.4  2072.2   325.5 2073.71
     332 2076.34   337.5 2080.08     339 2080.26   342.1 2082.41   344.9  2082.8
   349.9 2084.53   360.4 2084.25   374.1 2091.06   387.8 2096.38   415.2 2102.46
#Mann= 7 ,-1,0
       0      .1       0      40     .06       0  215.86      .1       0
  255.86     .06       0  266.03    .045       0   283.2     .06       0
  381.97      .1       0
Bank Sta=266.03,283.2
XS Rating Curve= 0 ,0
Exp/Cntr(USF)=0,0
Exp/Cntr=0.3,0.1

Type RM Length L Ch R = 1 ,409     ,144.4,139.6,135.5
XS GIS Cut Line= 6
2252296.69942472614491.4977596612252310.50044173614370.048809911
2252288.41881451614343.3668436782252260.81678047614302.883860428
2252198.25216999614193.395792093 2252125.5668137614152.912808842
#Sta/Elev= 30
       0 2085.38    21.4 2085.66    30.5 2084.83    37.8 2082.83    50.6 2078.53
    58.7 2076.53    62.7 2075.92    70.8 2075.55   106.5 2072.12   125.9  2071.3
   147.2 2071.56   169.2 2071.11   245.6 2071.36   249.4 2070.66   251.5 2069.44
     255 2066.88   257.3  2065.6   258.7 2065.14   263.2 2064.73   271.2 2065.12
   274.9 2065.78   283.7 2066.56   286.7 2067.43   295.5  2071.4   304.3 2073.55
   309.2 2073.99   407.6 2073.89   412.2 2074.06   413.1 2074.66   415.2 2075.19
#Mann= 6 ,-1,0
       0      .1       0      20     .06       0  235.86     .07       0
   258.7    .045       0   271.2     .07       0  309.04     .06       0
Bank Sta=258.7,271.2
XS Rating Curve= 0 ,0
Exp/Cntr(USF)=0,0
Exp/Cntr=0.3,0.1

Type RM Length L Ch R = 1 ,270     ,208.5,217.6,212.1
XS GIS Cut Line= 4
2252360.50176604614386.542650401 2252377.6456256614164.722542605
2252235.07806138614112.4015150462252121.77766991614110.551450893
#Sta/Elev= 30
       0 2072.49    69.6 2069.21    93.6 2069.53   109.7 2068.51   125.7 2068.36
   185.9 2064.82     210 2064.89   236.8 2065.52   262.4 2064.81   275.2 2065.37
   279.4 2065.12   286.3 2062.23     288 2061.67   290.8 2061.65   296.5 2061.67
   299.8 2062.26     305 2063.21   317.8 2063.35   330.6 2064.86   347.6 2064.53
   381.3 2065.51   409.3 2067.66   413.3  2068.3   421.3 2071.53   425.3 2072.18
   441.3 2070.22   461.3  2070.6   465.3 2071.27   473.3 2073.81   487.7 2074.38
#Mann= 6 ,-1,0
       0     .07       0     110     .06       0     210      .1       0
   286.3    .045       0   299.8     .07       0  404.35     .06       0
#XS Ineff= 2 , 0
           272.2 2067.37  335.02         2067.06
Permanent Ineff=
       F       F
Bank Sta=286.3,299.8
XS Rating Curve= 0 ,0
Exp/Cntr(USF)=0,0
Exp/Cntr=0.3,0.1

Type RM Length L Ch R = 1 ,52      ,,,
XS GIS Cut Line= 4
2252514.93667178614186.5568052142252384.14091064613963.804795266
2252167.99308519613953.2241324822252015.32923644613998.816499874
#Sta/Elev= 30
       0 2065.64    14.7 2064.22    24.8 2065.45   117.6 2064.97   155.5 2061.49
   191.8  2063.9   204.7 2063.86   225.1 2061.35   239.7 2060.59   276.1 2061.05
     299 2063.23   314.3 2061.13   330.4 2061.47  347.322057.711   354.4 2056.75
  366.352057.711   374.4 2058.68   382.4 2061.07   398.4 2061.97   458.5 2061.71
   503.5 2060.35     558 2060.81   562.2 2061.88   574.7 2071.44   578.9 2073.89
   591.4 2075.36   612.3 2075.47   616.5 2079.02   620.6 2084.16     634 2095.55
#Mann= 6 ,-1,0
       0     .06       0      20      .1       0  347.32    .045       0
  366.35      .1       0  534.72     .06       0  604.72      .1       0
Bank Sta=347.32,366.35
XS Rating Curve= 0 ,0
Exp/Cntr(USF)=0,0
Exp/Cntr=0.3,0.1
LCMann Table=0

Chan Stop Cuts=-1
Use User Specified Reach Order=0
Composite Channel Slope=5